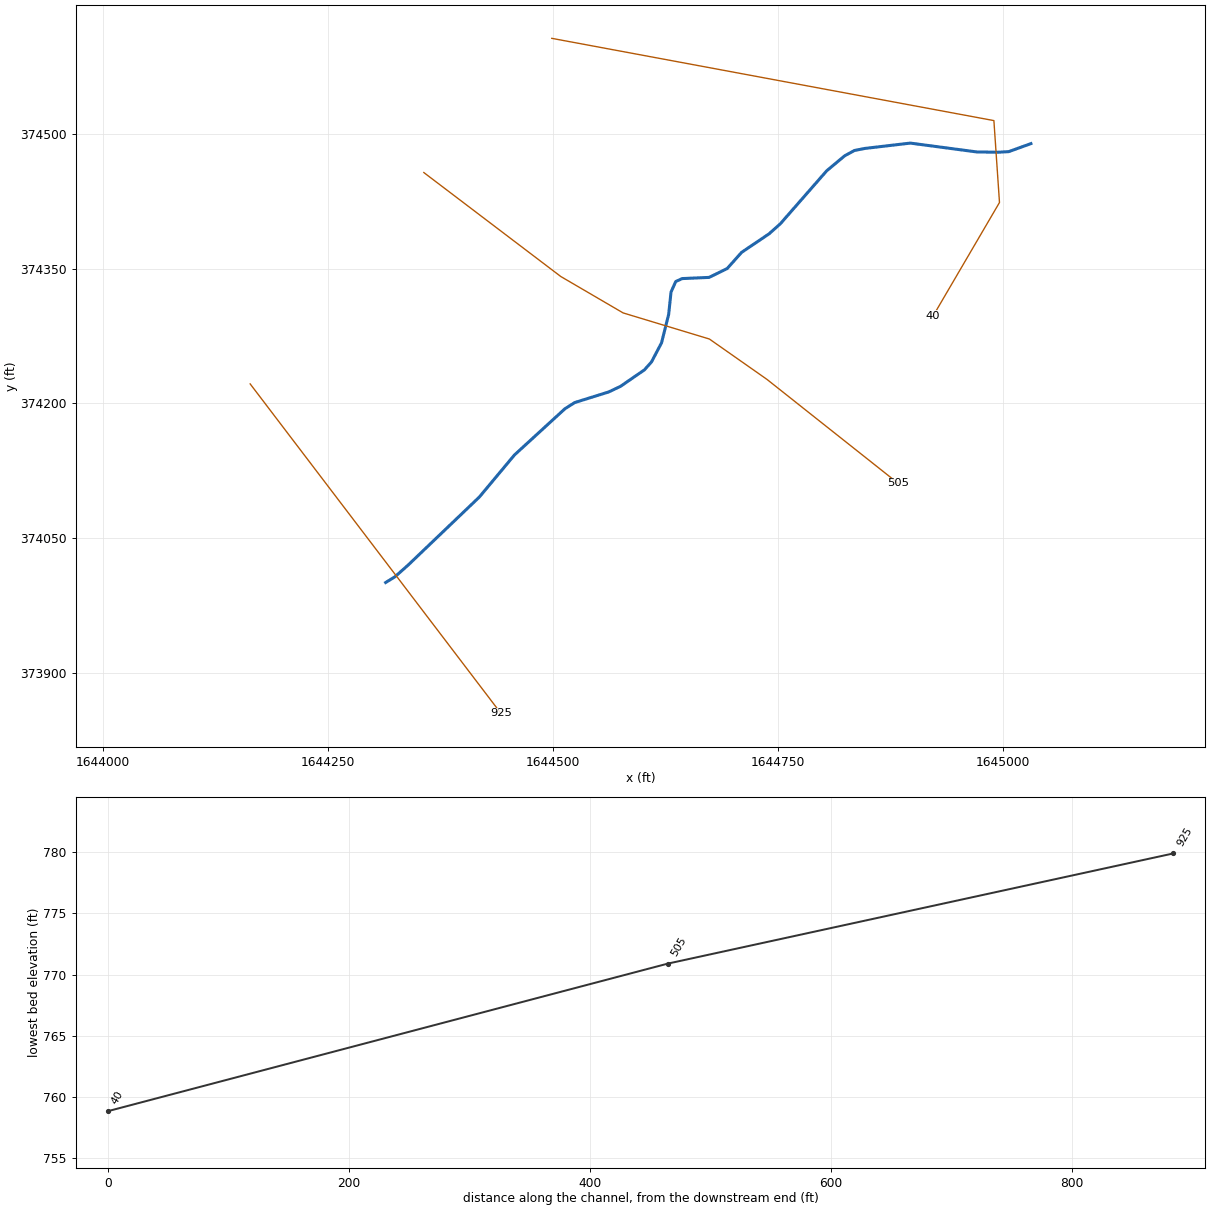
--- BUFALORNT1.prj (project) ---

Proj Title=BUFALORNT1
Current Plan=p01
Default Exp/Contr=0.3,0.1
English Units
Geom File=g01
Flow File=f01
Plan File=p01
Y Axis Title=Elevation
X Axis Title(PF)=Main Channel Distance
X Axis Title(XS)=Station
BEGIN DESCRIPTION:
---------- MODELED AS PART OF WVEMD CTP PROGRAM, 2023----------
Stream Name: Buffalo Run Tributary 1
Flood Zone:  AFH
Wetzel County, WV
HEC-RAS Version: RAS 6.3
Vertical Datum: NAVD88
Projection: NAD 1983 StatePlane West Virginia S FIPS 4702 (US Feet)
Terrain: 1-meter West Virginia FEMA R3 South Central (collected 2018-2020)
Land Use: 2019 NLCD
Hydrologic Method:
WV SIR2010-5033 regression equations
Additional Model Notes:
None
END DESCRIPTION:
DSS Export Rating Curves= 0
DSS Export Rating Curve Sorted= 0
DSS Export Volume Flow Curves= 0
DXF OffsetX= 0
DXF OffsetY= 0
DXF ScaleX= 1
DXF ScaleY= 10

--- BUFALORNT1.p01 (plan) ---

Plan Title=Floodplain
Program Version=6.30
Short Identifier=Floodplain
Geom File=g01
Flow File=f01
Subcritical Flow
K Sum by GR= 0
Std Step Tol= 0.01
Critical Tol= 0.01
Num of Std Step Trials= 20
Max Error Tol= 0.3
Flow Tol Ratio= 0.001
Split Flow NTrial= 30
Split Flow Tol= 0.02
Split Flow Ratio= 0.02
Log Output Level= 0
Friction Slope Method= 1
Unsteady Friction Slope Method= 2
Unsteady Bridges Friction Slope Method= 1
Parabolic Critical Depth
Global Vel Dist= 0 , 0 , 0
Global Log Level= 0
CheckData=True
Encroach Param=-1 ,0,0, 0
Computation Interval=1MIN
Output Interval=1HOUR
Instantaneous Interval=1HOUR
Mapping Interval=1HOUR
Computation Time Step Use Courant=        0
Computation Time Step Use Time Series=    0
Computation Time Step Count To Double=0
Computation Time Step Max Doubling=0
Computation Time Step Max Halving=0
Computation Time Step Residence Courant=0
Run HTab= 0
Run UNet= 0
Run Sediment= 0
Run PostProcess= 0
Run WQNet= 0
Run RASMapper=-1
UNET Theta= 1
UNET Theta Warmup= 1
UNET ZTol= 0.02
UNET ZSATol= 0.02
UNET MxIter= 20
UNET Max Iter WO Improvement= 0
UNET MaxInSteps= 0
UNET DtIC= 0
UNET DtMin= 0
UNET MaxCRTS= 20
UNET WFStab= 2
UNET SFStab= 1
UNET WFX= 1
UNET SFX= 1
UNET Gravity=32.17405
UNET 1D Methodology=Finite Difference
UNET DSS MLevel= 4
UNET Pardiso=0
UNET DZMax Abort= 100
UNET Use Existing IB Tables=-1
UNET Froude Reduction=False
UNET Froude Limit= 0.8
UNET Froude Power= 4
UNET D1 Cores= 0
UNET WindReference=Eulerian
UNET WindDragFormulation=Hsu (1988)
UNET D2 Coriolis=0
UNET D2 Cores= 0
UNET D2 Theta= 1
UNET D2 Theta Warmup= 1
UNET D2 Z Tol= 0.01
UNET D2 Volume Tol= 0.01
UNET D2 Max Iterations= 20
UNET D2 Equation= 0
UNET D2 RampUpFraction=0.1
UNET D2 TimeSlices= 1
UNET D2 Turbulence Formulation=None
UNET D2 Eddy Viscosity=0.3
UNET D2 Transverse Eddy Viscosity=0.1
UNET D2 Smagorinsky Mixing=0.05
UNET D2 BCVolumeCheck=0
UNET D2 Cores=0
UNET D2 SolverType=PARDISO (Direct)
UNET D2 Minimum Iterations= 3
UNET D2 Maximum Iterations= 30
UNET D2 Restart Number= 10
UNET D2 Relaxation Coeff=1.3
UNET D2 SOR Precondition Iterations= 10
UNET D2 ILUT Maximum Fill= 8
UNET D2 ILUT Tolerance=1E-08
UNET D2 Convergence Tolerance=0.00001
UNET D1D2 MaxIter= 0
UNET D1D2 ZTol=0.01
UNET D1D2 QTol=0.1
UNET D1D2 MinQTol=1
Write IC File= 0
Write IC File at Fixed DateTime=0
Write IC File at Sim End=0
Echo Input=False
Echo Parameters=False
Echo Output=False
Write Detailed= 0
HDF Write Warmup=0
HDF Write Time Slices=0
HDF Flush=0
HDF Compression= 1
HDF Chunk Size= 1
HDF Spatial Parts= 1
HDF Use Max Rows=0
HDF Fixed Rows= 1
Calibration Method= 0
Calibration Iterations= 20
Calibration Max Change=0.05
Calibration Tolerance=0.2
Calibration Maximum=1.5
Calibration Minimum=0.5
Calibration Optimization Method= 1
WQ AD Non Conservative
WQ ULTIMATE=-1
WQ Max Comp Step=1HOUR
WQ Output Interval=15MIN
WQ Output Selected Increments= 0
WQ Output face flow=0
WQ Output face velocity=0
WQ Output face area=0
WQ Output face dispersion=0
WQ Output cell volume=0
WQ Output cell surface area=0
WQ Output cell continuity=0
WQ Output cumulative cell continuity=0
WQ Output face conc=0
WQ Output face dconc_dx=0
WQ Output face courant=0
WQ Output face peclet=0
WQ Output face adv mass=0
WQ Output face disp mass=0
WQ Output cell mass=0
WQ Output cell source sink temp=0
WQ Output nsm pathways=0
WQ Output nsm derived pathways=0
WQ Create Restart=0
WQ Fixed Restart=0
WQ System Summary=0
WQ Write To DSS=0
Sorting and Armoring Iterations= 10
XS Update Threshold= 0.02
Bed Roughness Predictor= 0
Hydraulics Update Threshold= 0.02
Energy Slope Method= 1
Volume Change Method= 1
Sediment Retention Method= 0
Sediment TS Multiplier= 1
Warm Up Method= 0
XS Weighting Method= 0
Number of US Weighted Cross Sections= 1
Number of DS Weighted Cross Sections= 1
Upstream XS Weight=0
Main XS Weight=1
Downstream XS Weight=0
Number of DS XS's Weighted with US Boundary= 1
Upstream Boundary Weight= 1
Weight of XSs Associated with US Boundary= 0
Number of US XS's Weighted with DS Boundary= 1
Downstream Boundary Weight= 0.5
Weight of XSs Associated with DS Boundary= 0.5
Percentile Method= 0
Sediment Output Level= 3
Mass or Volume Output= 0
Output Increment Type= 1
Profile and TS Output Increment= 1
Transport Output Increment 1
XS Output Flag= 0
XS Output Increment= 10
Read HDF5 Sediment Hotstart= 0
Sediment Hotstart Type= 0
Write Gradation File= 0
Read Gradation Hotstart= 0
Write HDF5 File= 1
Write Binary Output= 1
Write DSS Sediment File= 0
DSS Sediment Output Type= 1
SV Curve= 0
Specific Gage Flag= 0
Subcell Erosion Methods= 0
Subcell Deposition Methods= 0
Advection Scheme= 1
Matrix Solver= 0
Implicit Weighting Factor= 1
Maximum Outer Loop Convergence Iterations= 5
Convergence Maximum Absolute= 0.001
Convergence RMSE= 0.0001
Grain Fractions Max Abs Error= 0.001
Max Subgrid Regions= 1
Max Subgrid Length Scale= 3.402823E+38
Initial Layer Thickness= 3.402823E+38
Min Layer Thickness= 3.402823E+38
Max Layer Thickness= 3.402823E+38
Number of Layers= 5

--- BUFALORNT1.f01 (steady flow) ---

Flow Title=Flow
Program Version=6.31
Number of Profiles= 1
Profile Names=F01pct
River Rch & RM=BUFALORNT1,Main,925
     564
Boundary for River Rch & Prof#=BUFALORNT1,Main            , 1
Up Type= 0
Dn Type= 3
Dn Slope=0.02586
DSS Import GetInterval= 0
DSS Import GetPeak= 0
DSS Import FillOption= 0

--- BUFALORNT1.g01 (geometry) ---

Geom Title=Geometry
Program Version=6.30

River Reach=BUFALORNT1      ,Main
Reach XY= 30
1644314.30769597 374000.405840651644324.48385672374006.642704815
1644339.25515264374019.7729278951644418.36457448374095.599875972
 1644457.4268323374142.540070817 1644513.5586098374194.076056972
1644524.39093722374200.9694158881644562.14020555 374212.78664948
1644575.27042864374219.0235136451644601.85895814374237.405694723
1644609.73722322374246.2685378941644620.89796205374267.605109394
1644628.77589905374299.1178416461644631.40187806374324.064970225
1644636.65416414374335.8822038171644643.87560639 374339.16467756
1644673.74693772374340.4776670631644693.77051972374350.325416386
1644709.85480514374368.3795141431644740.38263123374389.059590891
1644752.85635956374400.2203297321644804.39234573374459.306169555
1644824.41592772374476.0469497291644835.24825513374481.955730557
1644847.06548873374484.2532981491644897.28848539374490.162078977
1644971.14562114374480.3143296391644995.10817164374479.986246318
1645006.59732188374480.6427410541645031.28794788374489.569109122

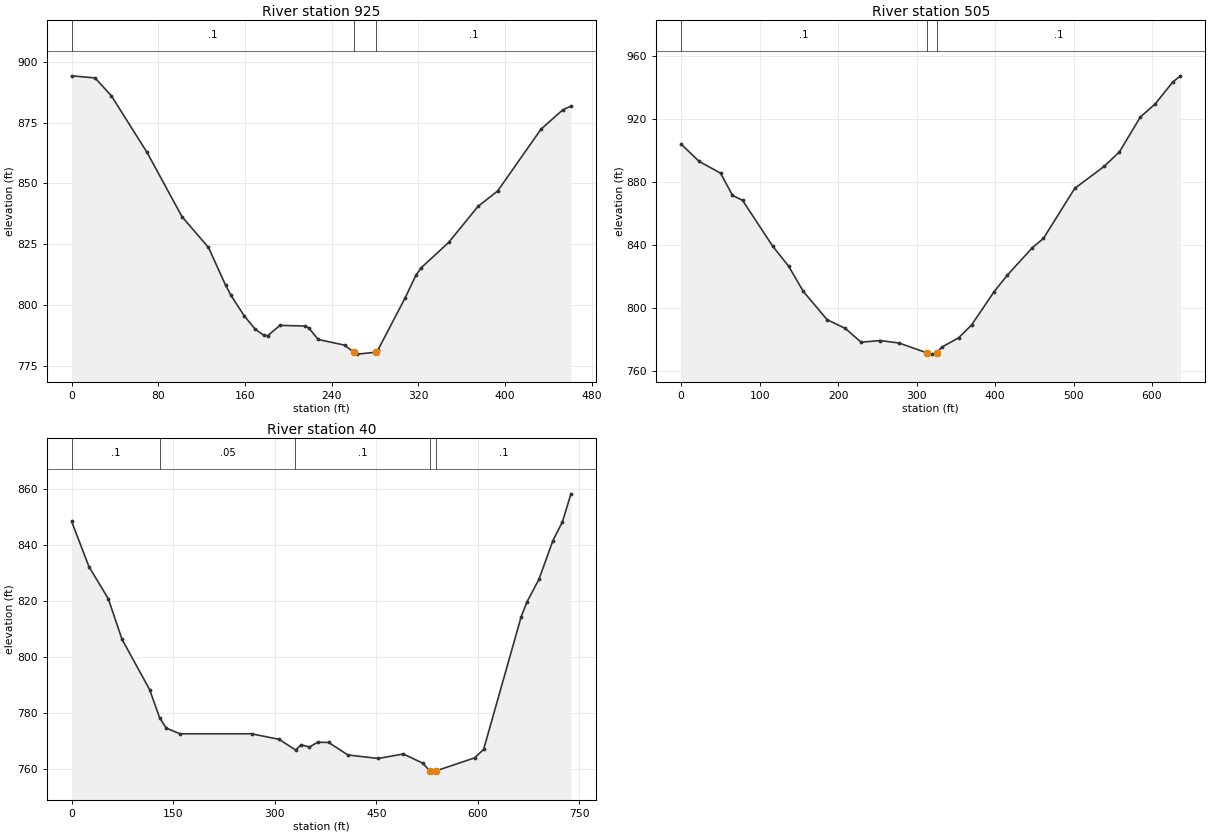
Type RM Length L Ch R = 1 ,925     ,413.8,419.6,422
XS GIS Cut Line= 2
 1644163.8027473374221.7494132941644442.42221144373854.536663322
#Sta/Elev= 30
       0  894.22    21.6  893.35    36.7  886.01    69.6  862.77   101.9  836.35
   126.3  823.74   142.1  808.23   147.1  804.04   159.3  795.63   169.5  790.11
   177.3  787.69   180.9  787.46   192.3  791.72   215.2  791.46   218.9  790.69
   227.5  785.94     252   783.6   260.3780.7304   263.7  779.91   280.7780.6866
   282.7   781.6   307.8  802.96   317.8  812.34   322.9  815.49     348  825.78
   375.1   840.6   393.2  846.91   433.3  872.34   453.4  880.27   460.9  881.77
#Mann= 3, -1 ,  0
       0     0.1       0   260.3   0.045       0   280.7     0.1       0
Bank Sta=260.3,280.7
XS Rating Curve= 0 ,0
Exp/Cntr(USF)=0,0
Exp/Cntr=0.3,0.1

Type RM Length L Ch R = 1 ,505     ,472.5,464.9,460.2
XS GIS Cut Line= 6
1644356.77020951374457.3304517571644508.93886842374341.466182172
1644578.19069843374300.8878512531644674.04024425374271.797686338
1644737.85999851374226.9181829241644883.84297426374110.909884751
#Sta/Elev= 30
       0  904.31    22.9  893.36    50.3  885.87    65.4  871.79    78.3  868.59
   116.9  839.34     137  826.75   155.7  810.73   186.1  792.74   208.9  787.35
   229.4  778.47   253.6  779.54   277.8  777.94   313.3 771.694   319.6   770.9
   325.4771.6856   332.1  775.32   353.6  781.31     370  789.36   398.5  810.39
   415.8  821.19   447.6  838.55   461.6  844.39   501.5  876.22     539  890.17
   558.5  899.43   585.2  921.59     604  929.82   626.3  943.71   636.2  947.71
#Mann= 3, -1 ,  0
       0     0.1       0   313.3   0.045       0   325.4     0.1       0
Bank Sta=313.3,325.4
XS Rating Curve= 0 ,0
Exp/Cntr(USF)=0,0
Exp/Cntr=0.3,0.1

Type RM Length L Ch R = 1 ,40      ,,,
XS GIS Cut Line= 4
1644498.91648067374606.9376125641644990.16038933374515.255532093
 1644996.3822714374423.9692941261644922.62349987374297.503092483
#Sta/Elev= 30
       0  848.38    25.6  832.24    54.1   820.8    74.5  806.25   115.2  788.32
     130  778.23   139.6   774.6   159.9  772.53   265.7  772.53   306.4  770.55
   330.8  766.75     339   768.6   351.2  767.81   363.4   769.5   379.6  769.43
   408.1  764.96   452.9  763.71     490  765.32   518.5  762.05   529.1  759.27
   534.5  758.83   537.9  759.26   595.2  763.91   608.6  766.96   664.1  814.38
   672.9  819.78   690.4  827.77   710.9  841.55   724.9   848.2   737.6  858.26
#Mann= 5, -1 ,  0
       0     0.1       0     130    0.05       0     330     0.1       0
   529.1   0.045       0   537.9     0.1       0
Bank Sta=529.1,537.9
XS Rating Curve= 0 ,0
Exp/Cntr(USF)=0,0
Exp/Cntr=0.3,0.1
LCMann Table=0

Chan Stop Cuts=-1
Use User Specified Reach Order=0
Composite Channel Slope=5